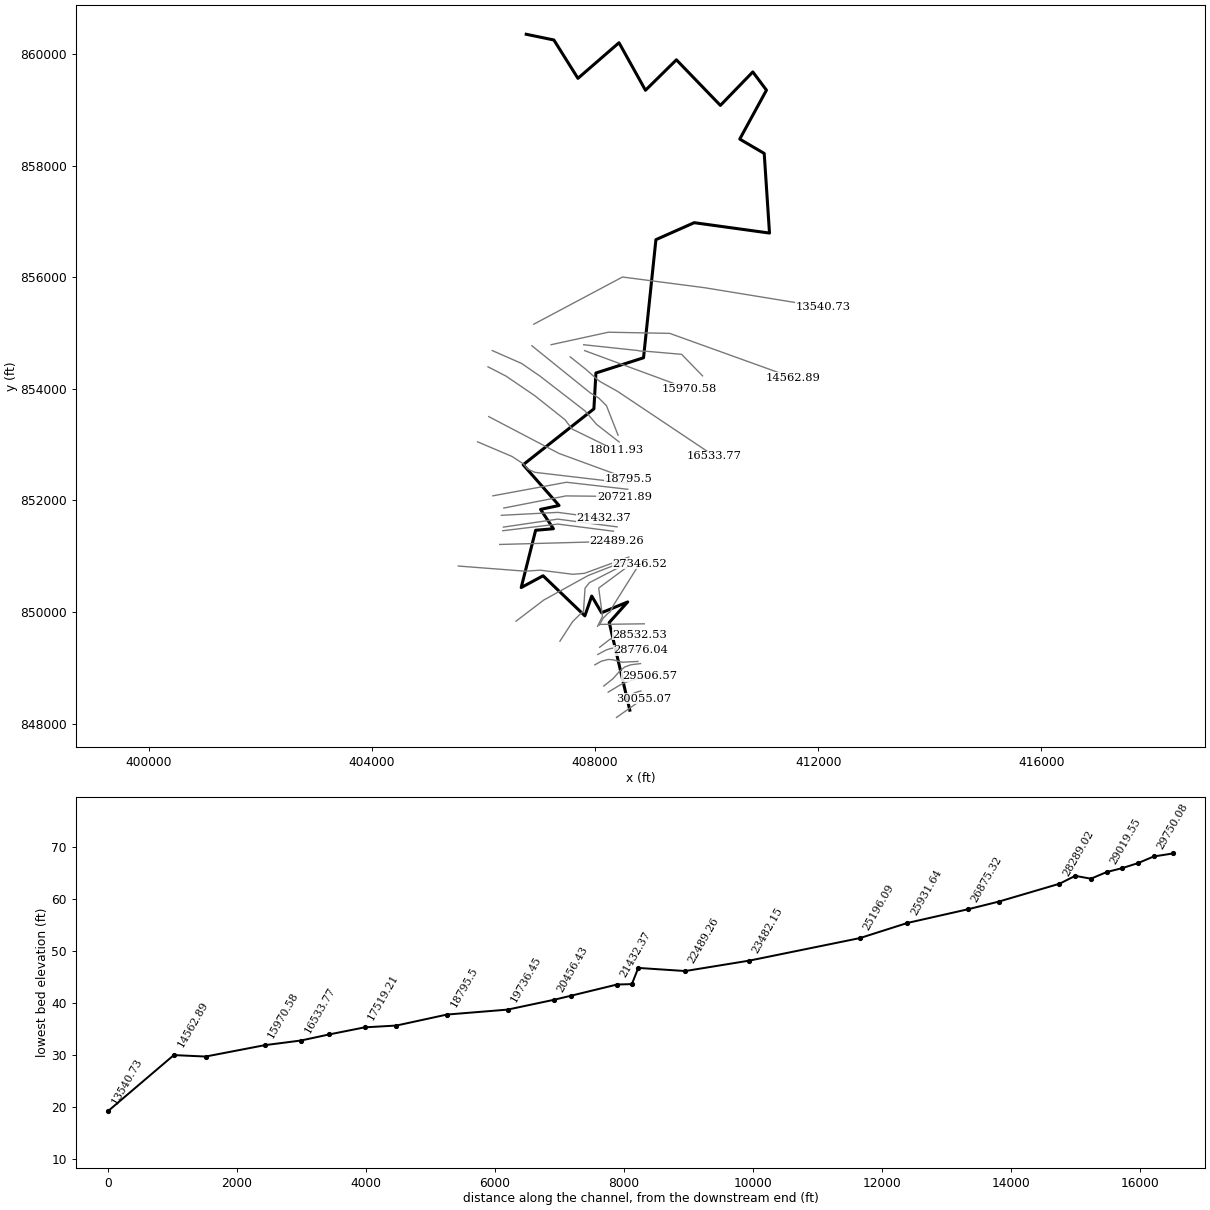
--- 7587_ras.prj (project) ---

Proj Title=7587
Current Plan=p01
Default Exp/Contr=0.3,0.1
English Units
Geom File=g01
Flow File=f01
Plan File=p01
Y Axis Title=Elevation
X Axis Title(PF)=Main Channel Distance
X Axis Title(XS)=Station
BEGIN DESCRIPTION:
RFD model 7587 exported to HEC-RAS
END DESCRIPTION:

--- 7587_ras.p01 (plan) ---

Plan Title=Plan 01
Program Version=4.10
Short Identifier=Plan 01
Geom File=g01
Flow File=f01
Subcritical Flow
Calc Critical at every XS
Secant Critical Depth

--- 7587_ras.f01 (steady flow) ---

Flow Title=Flow 01
Program Version=5.01
Number of Profiles= 6
Profile Names=10yr,25yr,50yr,100yr,100plus,500yr
River Rch & RM=7587,33,30055.07
 3531.57 5463.67 7234.72 8748.8312773.2913841.91
River Rch & RM=7587,33,29750.08
 3533.61 5466.97 7239.23 8754.4312781.4713850.01
River Rch & RM=7587,33,29506.57
 3538.14 5474.32 7249.27 8766.8812799.6413868.01
River Rch & RM=7587,33,29263.06
 3541.76  5480.2 7257.28 8776.8312814.17 13882.4
River Rch & RM=7587,33,29019.55
 3544.02 5483.87 7262.29 8783.0412823.2413891.39
River Rch & RM=7587,33,28776.04
 3553.14 5498.62  7282.4 8807.9612859.6313927.34
River Rch & RM=7587,33,28532.53
 3554.93 5501.53 7286.39 8812.9212866.8713934.52
River Rch & RM=7587,33,28289.02
 3560.55 5510.65 7298.86 8828.4112889.4713956.96
River Rch & RM=7587,33,27346.52
 3560.99 5511.38 7299.85 8829.6412891.2813958.76
River Rch & RM=7587,33,26875.32
 3606.87 5585.97 7401.83 8956.3513076.2614142.24
River Rch & RM=7587,33,25931.64
 3784.85 5873.49 7793.44  9441.3 13784.314835.54
River Rch & RM=7587,33,25196.09
 3811.55    5917 7853.03 9515.4413892.5514942.28
River Rch & RM=7587,33,23482.15
 4339.67 6770.69 9016.5510957.0315997.26   16974
River Rch & RM=7587,33,22489.26
 4350.78 6788.86 9041.4810988.1216042.6517018.02
River Rch & RM=7587,33, 21760.3
 4374.47 6827.58 9094.6311054.3616139.3717111.73
River Rch & RM=7587,33,21432.37
 4384.87 6844.61 9118.0211083.56   1618217153.13
River Rch & RM=7587,33,20721.89
 4385.49 6845.63 9119.4311085.3116184.5617155.61
River Rch & RM=7587,33,20456.43
 4394.03  6859.6 9138.6311109.2616219.5217189.52
River Rch & RM=7587,33,19736.45
 4404.59 6876.92 9162.4311138.9916262.9217231.68
River Rch & RM=7587,33, 18795.5
 4415.72 6895.19 9187.58 11170.416308.7817276.26
River Rch & RM=7587,33,18011.93
 4450.33 6951.89 9265.4911267.6416450.7517413.86
River Rch & RM=7587,33,17519.21
 4454.24  6958.3 9274.3211278.6616466.8517429.49
River Rch & RM=7587,33,16972.72
 4527.88 7079.39 9441.1211487.2416771.3817725.39
River Rch & RM=7587,33,16533.77
 4535.42 7091.78 9458.1811508.5816802.5317755.61
River Rch & RM=7587,33,15970.58
 4544.33 7106.46 9478.41 11533.916839.4917791.52
River Rch & RM=7587,33,15055.61
 6004.66 9416.1212584.7715335.9822390.5322789.29
River Rch & RM=7587,33,14562.89
 6010.01 9424.9312596.9315351.1922412.7422810.01
River Rch & RM=7587,33,13540.73
 6022.03 9444.7312624.2415385.3922462.6722856.61
River Rch & RM=7587,33,10213.72
  6378.610029.4313428.7516390.0823929.5224211.02
River Rch & RM=7587,33,7228.789
 6388.1510045.18 13450.516417.3323969.3124247.87
River Rch & RM=7587,33,  50.451
 6034.36 9465.0812652.34 15420.622514.0722904.64
Boundary for River Rch & Prof#=7587,33,1
Up Type= 0
Dn Type= 2
Boundary for River Rch & Prof#=7587,33,2
Up Type= 0
Dn Type= 2
Boundary for River Rch & Prof#=7587,33,2
Up Type= 0
Dn Type= 2
Boundary for River Rch & Prof#=7587,33,2
Up Type= 0
Dn Type= 2
Boundary for River Rch & Prof#=7587,33,2
Up Type= 0
Dn Type= 2
Boundary for River Rch & Prof#=7587,33,2
Up Type= 0
Dn Type= 2

--- 7587_ras.g01 (geometry) ---

Geom Title=7587
Program Version=4.10

River Reach=7587,33
Reach XY= 30
408624.357073605848240.281625628408255.699666202849810.929773763
408586.810777336850180.374218211408118.477443993 849986.48532933
407941.810777307850285.929773778407819.588555098849930.929773793
 407070.14411068850649.263107106 406677.92188862850437.596440434
406936.810777307851464.818662658 407255.14411068851492.040884897
 407025.14411068851838.707551554407356.810777336851908.707551554
406713.477443993852639.263107106407980.952908993 853640.53235966
408017.322012395854283.048647642408870.592027307854556.110329345
409092.443879187856672.950607106409778.588457167856977.087318406
411128.034156978856791.006162643411033.314543426858217.931828797
410594.706363231858475.415693387 411073.63027817859352.280147985
410829.066847563859678.982375219410247.729511201859079.304582268
409459.535066783859895.971248955408905.368400276859350.137915596
408431.062844545 860202.22124894 407694.95173341859564.026804477
  407263.8809461860251.401314348406768.281282753860353.856685057

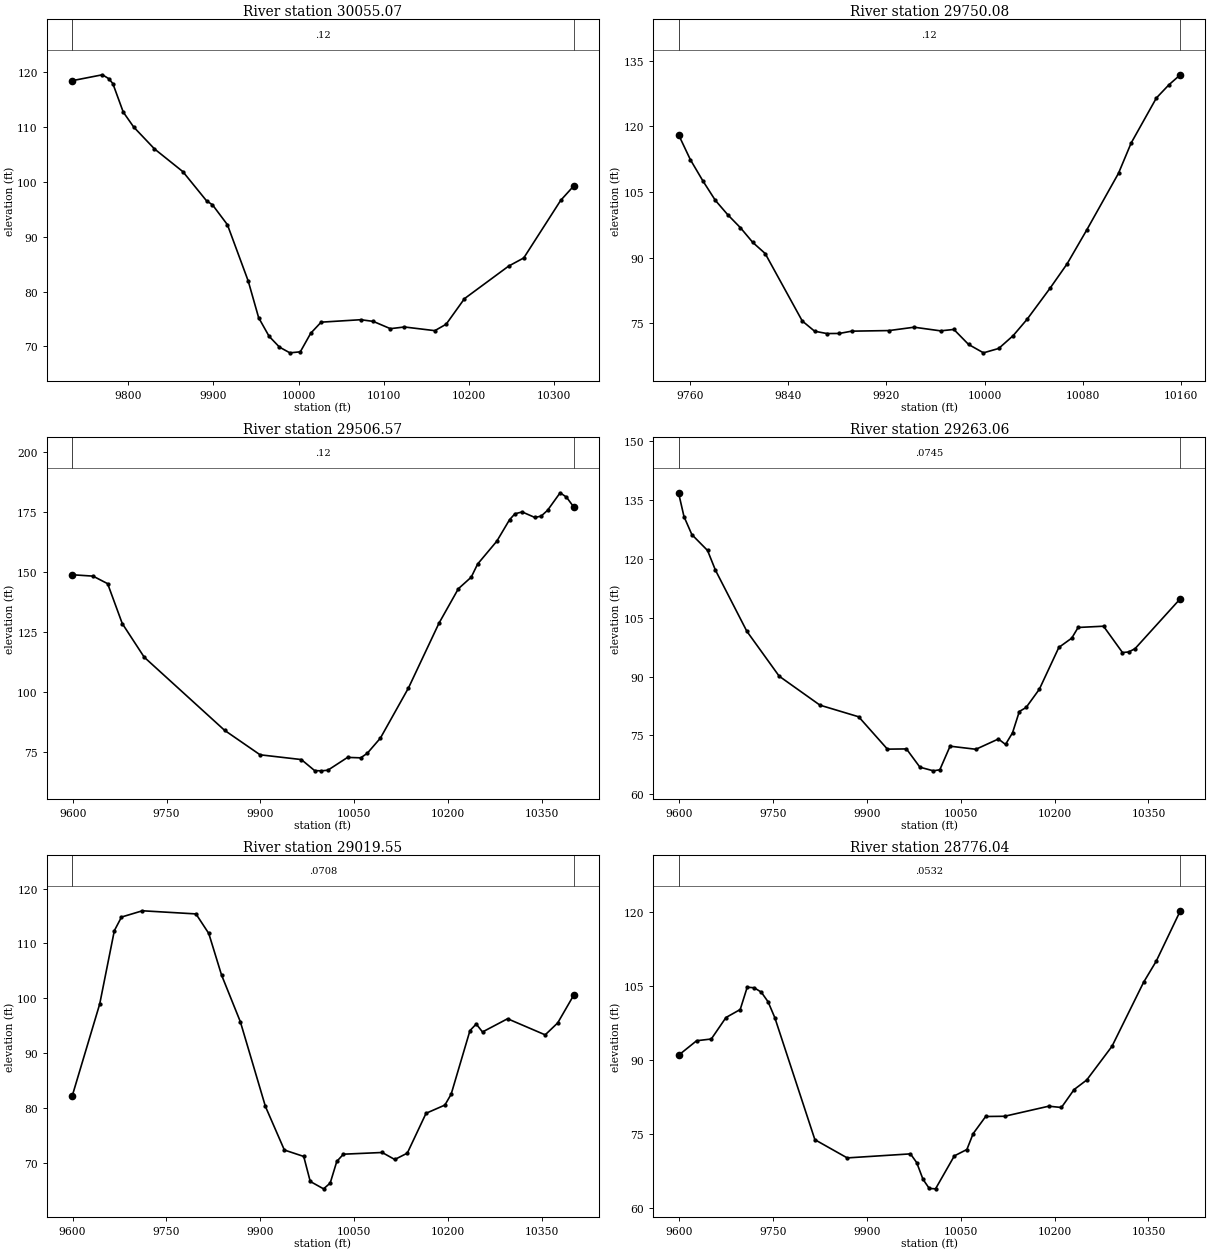
Type RM Length L Ch R = 1 ,30055.07,304.989800,304.989800,304.989800
XS GIS Cut Line= 2
408385.860839635848110.256770924408867.631672978 848448.79843758
#Sta/Elev= 30
9734.107118.44419769.721119.52499777.143118.81749781.943117.92479794.165112.7234
9806.388110.00379830.832106.00569864.108101.86639891.94296.537869898.89495.81268
9916.38692.19088 9940.8381.911489953.05275.228479965.27471.847239977.49769.86497
9989.71968.8246410001.9469.0112310014.1672.3972710026.3874.4176210072.8274.86551
 10087.5 74.560110107.6173.2309410124.1673.5377310159.7972.8700510173.0574.03913
10194.5778.7038510246.3884.6370710264.15 86.129710307.4996.6287510322.9399.27868
#Mann= 3 , 0 , 0
9734.107    0.12       09734.107    0.12       010322.93    0.12       0
#XS Ineff= 2 , 0
       0                               0
Bank Sta=9734.107,10322.93
Exp/Cntr=0.3,0.1

Type RM Length L Ch R = 1 ,29750.08,243.509300,243.509300,243.509300
XS GIS Cut Line= 6
408435.540779352848472.219897851408627.503336281848503.407087192
408656.080376893848515.438702554408710.752928555848550.467679322
408776.919730932848573.165159792408823.994213969848584.418461412
#Sta/Elev= 30
9750.529118.08349760.174112.36779770.371107.52379780.568103.06329790.76599.75328
9800.96196.829529811.07493.458749821.15190.930919851.38375.522849861.46173.18001
9871.53872.643929881.615 72.66929891.69373.190059922.16973.327229942.59374.09318
9964.13373.260629974.98373.58436 9986.9870.158249999.12168.2385610011.5669.23969
10023.3372.1658410034.68 75.899210053.4883.02455 10067.3 88.562710083.1696.22606
10109.22109.261410119.53116.172210140.09126.457210150.37129.486610159.62131.7603
#Mann= 3 , 0 , 0
9750.529    0.12       09750.529    0.12       010159.62    0.12       0
#XS Ineff= 2 , 0
       0                               0
Bank Sta=9750.529,10159.62
Exp/Cntr=0.3,0.1

Type RM Length L Ch R = 1 ,29506.57,243.509300,243.509300,243.509300
XS GIS Cut Line= 6
408236.343999673848562.950389605408447.069157127848690.224023052
408555.070214291848742.978732157408775.632700232848811.481304699
408883.532435191848834.455760362 408976.68355799848847.834539358
#Sta/Elev= 30
9599.042148.83659632.519148.25989655.884145.10819679.248128.46319714.296114.4284
9842.80283.874759899.52873.654429965.43371.667759986.67267.06475 9997.2966.95835
10007.8267.2209610039.3272.5707110060.3272.3868810070.8274.2844310091.8180.63596
10136.66101.569610185.46128.6328 10216.4142.997910236.93147.818710247.19153.3083
10277.82162.842310298.18 171.80910306.86 174.29810318.45175.054810338.65172.7444
10348.76173.325710358.86175.719610379.06 183.05910389.17181.227510400.97 177.073
#Mann= 3 , 0 , 0
9599.042    0.12       09599.042    0.12       010400.97    0.12       0
#XS Ineff= 2 , 0
       0                               0
Bank Sta=9599.042,10400.97
Exp/Cntr=0.3,0.1

Type RM Length L Ch R = 1 ,29263.06,243.509300,243.509300,243.509300
XS GIS Cut Line= 6
408158.062413198848673.700075594408326.874862718848807.512122622
408438.306982467848935.810356274408531.327584659849013.240334815
408641.077526791849053.444804049408817.065102247849075.232668689
#Sta/Elev= 30
9599.134136.78619607.844130.72719620.398126.14379645.506122.0979 9658.06117.0995
9708.276101.52759759.96490.093199825.15182.714689886.94479.757589932.88171.51878
9963.29871.577139984.81566.9230610006.4265.9958910016.6266.27031   1003372.27246
 10074.371.4870810110.2374.1043510121.5972.7153810132.7575.6658410143.64 81.0984
10154.53 82.131210175.6286.7685810206.8297.42004 10227.499.7803810237.58102.4942
10278.19102.818110308.4996.1130410318.5496.2650710328.5897.10586 10400.9109.8186
#Mann= 3 , 0 , 0
9599.134  0.0745       09599.134  0.0745       0 10400.9  0.0745       0
#XS Ineff= 2 , 0
       0                               0
Bank Sta=9599.134,10400.9
Exp/Cntr=0.3,0.1

Type RM Length L Ch R = 1 ,29019.55,243.509200,243.509200,243.509200
XS GIS Cut Line= 6
407997.753830345849052.842842428 408116.57393082849119.137082131
408237.689271254849149.385386683408316.620220359849144.932122721
408486.807226115849100.348758903408770.767079183849113.636183773
#Sta/Elev= 30
9599.132 82.08389643.287  98.9539666.671112.33859678.112114.8246 9711.54115.9687
9797.112115.39519817.562111.83189837.906104.26589868.05895.708059908.08980.25989
 9938.3472.314529969.27871.140559979.70666.5773710000.9965.2295510011.5766.27839
10022.1470.2380410032.7271.5517110094.6571.8624710114.7570.5834810134.7671.73977
10164.7679.0159210194.8180.5141910204.8382.49184 10234.994.1042810244.9295.30835
10254.9493.8548610295.0296.2677210355.1193.3273710375.1295.5087210400.92100.6095
#Mann= 3 , 0 , 0
9599.132  0.0708       09599.132  0.0708       010400.92  0.0708       0
#XS Ineff= 2 , 0
       0                               0
Bank Sta=9599.132,10400.92
Exp/Cntr=0.3,0.1

Type RM Length L Ch R = 1 ,28776.04,243.509300,243.509300,243.509300
XS GIS Cut Line= 6
408050.350742264849238.816278426408204.999098084849321.325149179
408285.652497993849346.096021173408375.293641732849360.612706591
 408518.73055085849356.993629728408823.056170144849314.301412887
#Sta/Elev= 30
9599.09591.011439627.99893.955249651.44994.307069674.90198.659669697.649100.2803
9708.853104.80269720.056104.68319731.259 103.8089742.121101.86249752.98498.61825
9816.99273.908039868.65670.217949969.72171.034759979.73569.256959989.74965.87959
9999.76264.0336110009.7863.9509310039.8370.6250610059.8771.9186910069.8875.13185
10089.9278.6080510120.1278.6517710190.7480.6947210210.9580.4299810231.1684.05685
10251.3785.9991610291.7992.8322110342.31105.804310362.52110.085410400.97120.2841
#Mann= 3 , 0 , 0
9599.095  0.0532       09599.095  0.0532       010400.97  0.0532       0
#XS Ineff= 2 , 0
       0                               0
Bank Sta=9599.095,10400.97
Exp/Cntr=0.3,0.1

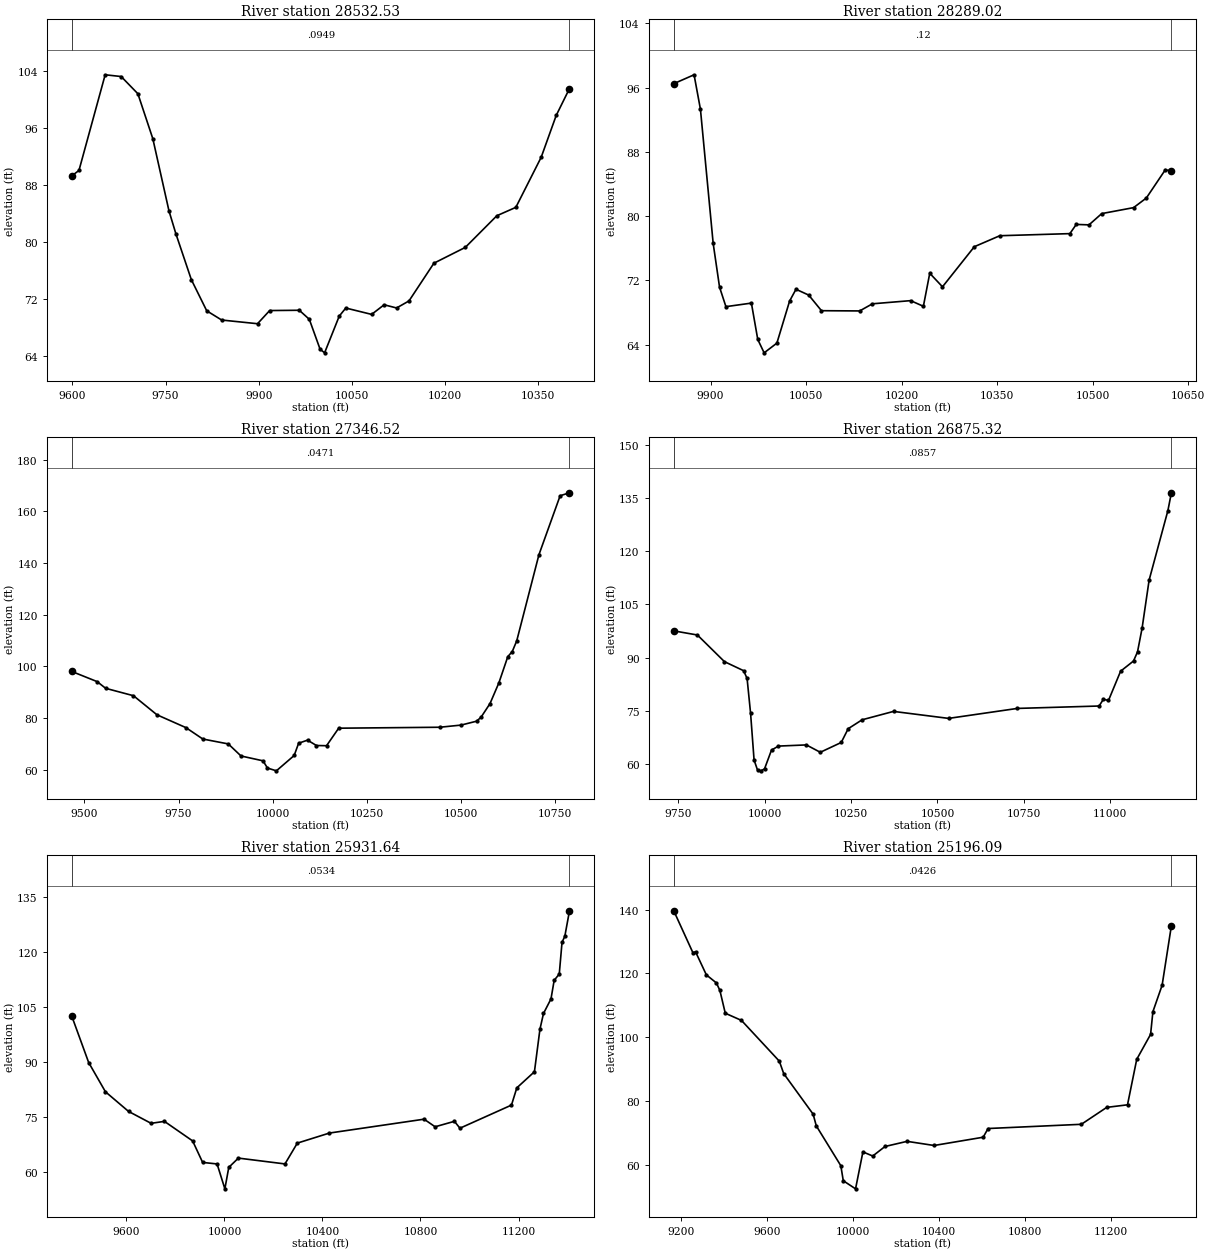
Type RM Length L Ch R = 1 ,28532.53,243.509300,243.509300,243.509300
XS GIS Cut Line= 6
408083.413996948849367.758232152408259.252845953849504.145706068
408457.501322177849623.907478824408512.267399125849633.687538465
408581.923850226849631.476279262408799.678412725849590.709153329
#Sta/Elev= 30
9599.05489.312769610.51290.072679652.718103.47859678.526103.23249705.444100.8178
9729.539 94.51089755.51884.406669766.75881.16796 9791.5774.762789816.383 70.3941
9840.43769.102429898.21368.585449917.79270.430569965.52770.471659981.67469.20303
    999965.0162810006.2864.5036810029.9369.6575910040.4570.7835810082.0669.89301
10102.2371.2387410122.2770.7917910142.2871.7799410182.4177.0672510233.01 79.2839
10283.8383.7202510314.4584.8975110355.2991.9182210379.5297.7844210400.89101.5537
#Mann= 3 , 0 , 0
9599.054  0.0949       09599.054  0.0949       010400.89  0.0949       0
#XS Ineff= 2 , 0
       0                10067.84       0
Bank Sta=9599.054,10400.89
Exp/Cntr=0.3,0.1

Type RM Length L Ch R = 1 ,28289.02,942.504800,942.504800,942.504800
XS GIS Cut Line= 2
408103.098976195849778.015740857408884.348976195849788.432407483
#Sta/Elev= 30
 9842.2596.476799874.15497.585929884.15593.294049904.15776.591699914.15871.15678
9924.15868.729739964.16269.171829974.16364.646939984.16462.9819810004.1764.19011
10024.1769.4330110034.1770.8931210054.1770.1688610074.1768.2269910134.1868.19681
10154.1869.0846310214.1869.4778910234.1968.7743610244.1972.8844210264.1971.19987
10314.1976.19038 10354.277.5567610464.2177.8181110474.2178.9634410494.2178.90837
10514.2180.3102710564.2281.0523410584.2282.2457810614.2285.7816910623.5785.56251
#Mann= 3 , 0 , 0
 9842.25    0.12       0 9842.25    0.12       010623.57    0.12       0
#XS Ineff= 2 , 0
       0                10136.21       0
Bank Sta=9842.25,10623.57
Exp/Cntr=0.3,0.1

Type RM Length L Ch R = 1 ,27346.52,471.199000,471.199000,471.199000
XS GIS Cut Line= 6
408078.197355837849765.248090357408144.802225053849885.365270361
408222.781397372849966.202324584408271.659207404 850002.52501528
408341.568130672850137.362002268408798.222003341850863.614293173
#Sta/Elev= 30
9466.67197.996769533.84794.070079556.33291.484939630.24988.613289692.46781.23451
9769.38576.265929814.262 71.85189881.847 69.95549915.63965.287919974.02463.41224
9985.83660.6207910009.4659.5365710056.7165.4777510068.5270.2233910092.1571.41838
10115.7769.3447210142.6669.2634110174.8476.0440310443.2476.41208 10499.677.24516
10541.03  78.75910552.8480.3270710576.4685.5624610600.0993.6077510623.71103.7498
10635.53105.706410647.34109.8219 10706.4143.223410762.61166.033610787.45167.1765
#Mann= 3 , 0 , 0
9466.671  0.0471       09466.671  0.0471       010787.45  0.0471       0
#XS Ineff= 2 , 0
       09854.464        10088.97       0
Bank Sta=9466.671,10787.45
Exp/Cntr=0.3,0.1

Type RM Length L Ch R = 1 ,26875.32,943.678100,943.678100,943.678100
XS GIS Cut Line= 4
408046.426522493849743.763715371 408134.96818918  849920.8470487
408067.151348889850429.310590371408653.088848889850863.338368148
#Sta/Elev= 30
9736.975 97.52899805.43996.361529883.70188.85314 9939.1586.300459949.23884.10434
9959.32774.290979969.41561.142939979.50458.262389989.59358.077539999.68158.63665
10019.8663.9289410040.0465.0566510120.7465.38281 10161.163.3081610221.6366.06804
10241.8169.9550710282.1672.4677110372.9674.8272910532.3672.8598310731.4875.67144
10967.9276.3486810980.3778.2551810995.0977.9140711030.1586.1544111067.4889.03242
 11079.191.6051211092.3798.30106 11112.7111.845211167.04131.435811177.11136.4484
#Mann= 3 , 0 , 0
9736.975  0.0857       09736.975  0.0857       011177.11  0.0857       0
#XS Ineff= 2 , 0
       0                10299.08       0
Bank Sta=9736.975,11177.11
Exp/Cntr=0.3,0.1

Type RM Length L Ch R = 1 ,25931.64,735.551500,735.551500,735.551500
XS GIS Cut Line= 6
 407372.29531005849476.908116281407597.690679014849825.079227403
407794.767123938   850021.572145407822.470843107850427.510755613
407900.245966971850525.664757028408612.051522523850893.720312595
#Sta/Elev= 30
9377.561102.41039446.10489.838989514.54681.867159608.75276.522159700.83773.27329
9755.35273.802879870.28568.483849911.18762.624419970.11862.2049810001.8955.42653
10017.8361.2789910057.0463.79983 10247.162.21147 10297.5 67.880710428.5470.62312
 10814.774.4008910859.7372.3310110938.5373.8191310961.0571.9402711171.3378.24052
 11193.182.93156   1126587.3219311287.5298.9302811301.96103.194611332.55107.1655
11345.51112.220511366.32113.943511377.58122.575111389.05124.244611408.04131.1694
#Mann= 3 , 0 , 0
9377.561  0.0534       09377.561  0.0534       011408.04  0.0534       0
#XS Ineff= 2 , 0
       09832.042        10340.51       0
Bank Sta=9377.561,11408.04
Exp/Cntr=0.3,0.1

Type RM Length L Ch R = 1 ,25196.09,1713.940000,1713.940000,1713.940000
XS GIS Cut Line= 4
406584.273744792849834.692534804407080.801522493850213.164757043
407879.412633598850654.136979282408605.107078046850938.859201476
#Sta/Elev= 30
9165.285139.62199254.215126.51869266.789126.76999317.084119.54159363.743117.0206
9379.953114.68239405.101107.52819480.543105.27469656.57792.519419677.16688.60448
9814.09475.902089828.67572.245319942.90759.76316 9954.33 55.051610011.4552.51455
10045.7264.0913310091.4162.7940210148.5265.7798210251.3367.3904410376.9966.09467
10605.4568.68417 10628.371.4121711062.37 72.731911180.5478.0350711277.2178.83674
11320.1893.0930711384.64100.899911395.38108.012711438.35116.301511481.43134.9256
#Mann= 3 , 0 , 0
9165.285  0.0426       09165.285  0.0426       011481.43  0.0426       0
#XS Ineff= 2 , 0
       09878.565        10259.61       0
Bank Sta=9165.285,11481.43
Exp/Cntr=0.3,0.1

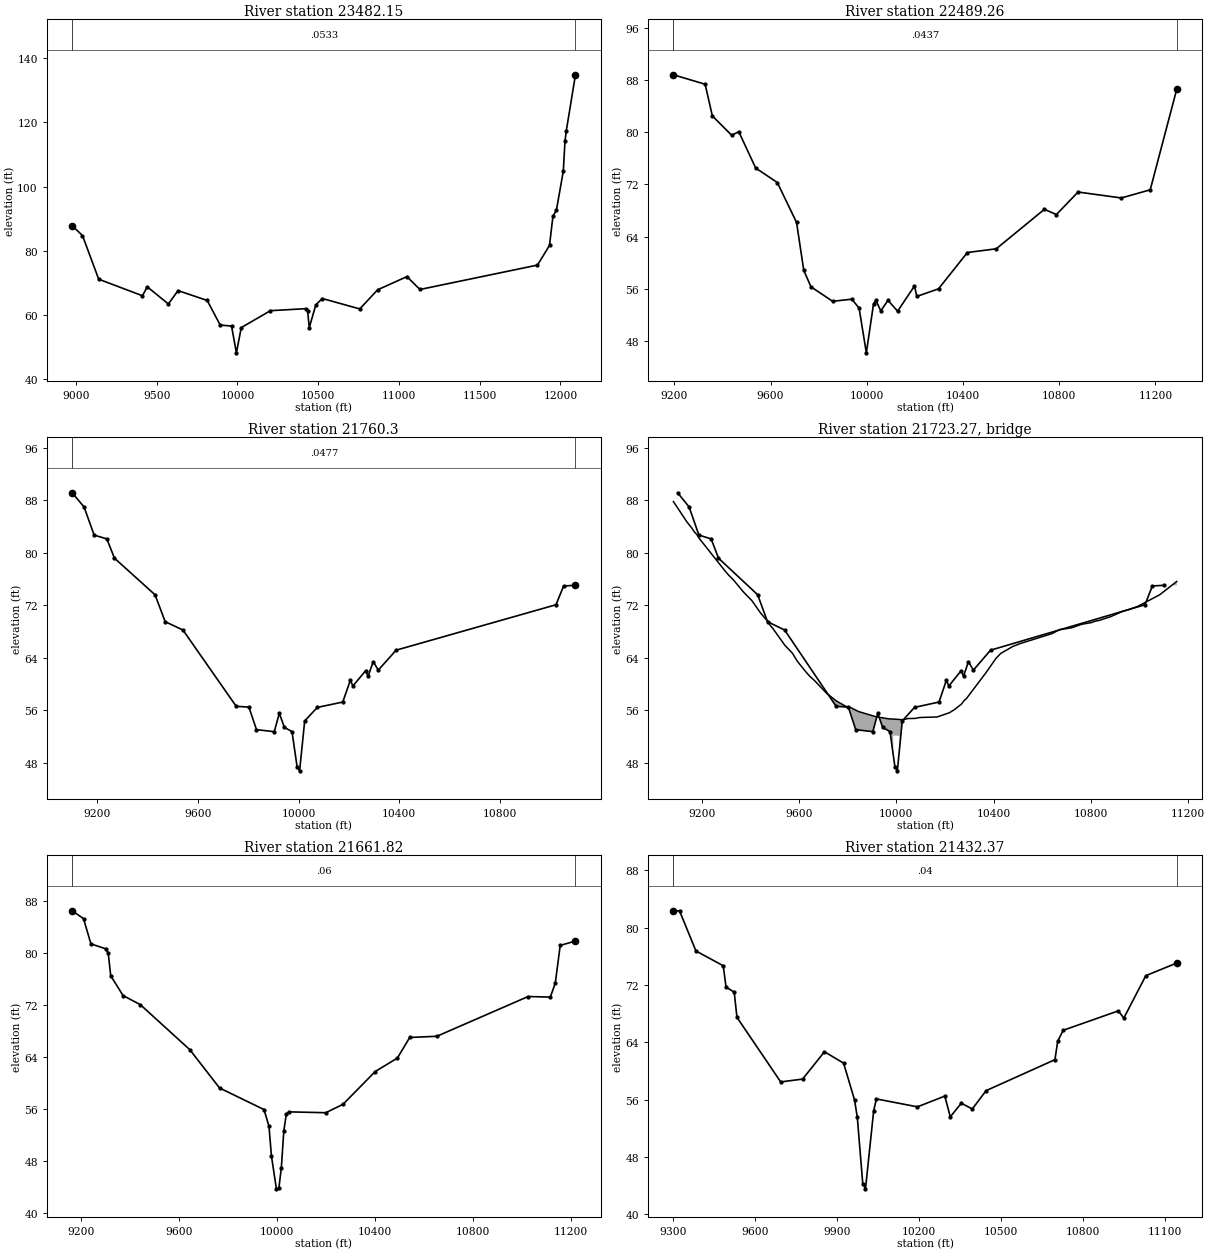
Type RM Length L Ch R = 1 ,23482.15,992.886900,992.886900,992.886900
XS GIS Cut Line= 6
405551.074761003850823.663587615406750.598518044850731.445679724
 407016.94880259850749.478414446407605.056441486850675.693692207
407811.219635934850693.054803327408605.924497068850984.576794073
#Sta/Elev= 30
8976.64787.832739040.74884.737639141.02371.135459411.76565.975419441.84768.75404
9572.241 63.40939632.42767.578759812.98464.497799893.23156.835799963.44856.51666
9993.54148.1725410023.6356.0342610204.1761.3181310424.6761.95092 10434.7 61.1316
10444.7256.0224610485.0263.1084110525.3465.1143910757.1461.86619   1086867.82719
11049.3771.9475611129.6567.9265311857.4575.5355811932.0181.6657811953.3290.75294
11974.6292.6539412017.23104.736412027.88114.169112035.93117.400712092.77134.8771
#Mann= 3 , 0 , 0
8976.647  0.0533       08976.647  0.0533       012092.77  0.0533       0
#XS Ineff= 2 , 0
       09888.223        10523.83       0
Bank Sta=8976.647,12092.77
Exp/Cntr=0.3,0.1

Type RM Length L Ch R = 1 ,22489.26,728.963900,728.963900,728.963900
XS GIS Cut Line= 2
406293.203142881851210.307407483408385.217031777851266.731018603
#Sta/Elev= 30
9196.23788.809549328.08287.359669358.09382.503419438.12279.542589468.13380.07021
9538.15874.508999628.19172.28649 9708.2266.159869738.23158.806949768.24256.28839
9858.27554.067619938.30454.393549968.31553.013989998.32646.1643810028.3453.67913
10038.3454.2069410058.3552.5949210088.3654.2222910128.3752.54643 10198.456.41207
 10208.454.8173710298.4355.9776910418.4861.5512210538.5262.1215310738.5968.17262
10788.6167.3724310878.6570.8270811058.7169.9163511178.7571.1697411289.01  86.598
#Mann= 3 , 0 , 0
9196.237  0.0437       09196.237  0.0437       011289.01  0.0437       0
#XS Ineff= 2 , 0
       0                10359.38       0
Bank Sta=9196.237,11289.01
Exp/Cntr=0.3,0.1

Type RM Length L Ch R = 1 , 21760.3,98.477500,98.477500,98.477500
XS GIS Cut Line= 3
406348.194933996851456.283690244407333.437989533 851575.64132911
408331.701878443851447.603134692
#Sta/Elev= 30
9100.63989.174829147.78687.020089188.07982.721399238.44482.141189268.66479.20016
9429.83373.619219470.12669.513859540.63868.242839752.17356.609629802.53956.48665
9832.75853.04724 9903.2752.736769923.41655.537699943.56253.391479973.78252.75068
9993.92847.39804   1000446.7654310024.1554.3763610074.5156.4437110175.3257.25847
10205.5660.5821410215.6459.7039810266.0562.0339210276.1361.19454 10296.363.42652
10316.4662.1224210387.0465.16592 11022.2 72.097611052.4474.9607411099.5375.06069
#Mann= 3 , 0 , 0
9100.639  0.0477       09100.639  0.0477       011099.53  0.0477       0
#XS Ineff= 2 , 0
       09952.591        10035.31       0
Bank Sta=9100.639,11099.53
Exp/Cntr=0.3,0.1

Type RM Length L Ch R = 3 ,21723.27,,,
BEGIN DESCRIPTION:
END DESCRIPTION:
Bridge Culvert--1,0,-1,-1, 0
Deck Dist Width WeirC Skew NumUp NumDn MinLoCord MaxHiCord MaxSubmerge Is_Ogee
37.263700,23.950100,2.6,0, 60, 60, , , 0.95, 0, 0,0,,
 9083.34 9139.06 9159.21 9169.29 9179.37 9189.45 9290.22 9310.38 9330.53 9370.84
 9406.51 9441.39 9471.62 9481.70 9491.77 9542.16 9572.39 9592.55 9622.78 9642.94
 9663.09 9713.48 9753.79 9794.10 9810.28 9844.49 9915.03 9965.58 9987.04 9987.04
10012.9610012.9610029.0310046.2910076.5910096.7410167.1910217.5110237.6410267.83
10277.8910287.9610368.4710408.7310428.8610479.1810509.3710640.2110670.4010720.72
10760.9810801.2310821.3610831.4310881.7510932.6910952.2010992.4511083.0311152.70
   87.83   84.72   83.78   83.21   82.82   82.22   77.50   76.61   75.87   74.06
   72.70   70.85   69.54   68.93   68.50   65.88   64.72   63.49   62.09   61.23
   60.55   58.58   57.41   56.56   56.44   55.81   55.03   54.71   54.66   54.66
   54.60   54.60   54.56   54.74   54.76   54.90   54.98   55.62   56.08   56.95
   57.46   57.79   61.74   63.88   64.67   65.75   66.18   67.70   68.30   68.58
   69.11   69.37   69.64   69.68   70.29   71.14   71.31   71.85   73.63   75.65
 -912.17 -915.28 -916.22 -916.79 -917.18 -917.78 -922.50 -923.39 -924.13 -925.94
 -927.30 -929.15 -930.46 -931.07 -931.50 -934.12 -935.28 -936.51 -937.91 -938.77
 -939.45 -941.42 -942.59 -943.44 -943.56 -944.19 -944.97 -945.29 -945.34   52.16
   52.10 -945.40 -945.44 -945.26 -945.24 -945.10 -945.02 -944.38 -943.92 -943.05
 -942.54 -942.21 -938.26 -936.12 -935.33 -934.25 -933.82 -932.30 -931.70 -931.42
 -930.89 -930.63 -930.36 -930.32 -929.71 -928.86 -928.69 -928.15 -926.37 -924.35
 9083.34 9139.06 9159.21 9169.29 9179.37 9189.45 9290.22 9310.38 9330.53 9370.84
 9406.51 9441.39 9471.62 9481.70 9491.77 9542.16 9572.39 9592.55 9622.78 9642.94
 9663.09 9713.48 9753.79 9794.10 9810.28 9844.49 9915.03 9965.58 9987.04 9987.04
10012.9610012.9610029.0310046.2910076.5910096.7410167.1910217.5110237.6410267.83
10277.8910287.9610368.4710408.7310428.8610479.1810509.3710640.2110670.4010720.72
10760.9810801.2310821.3610831.4310881.7510932.6910952.2010992.4511083.0311152.70
   87.83   84.72   83.78   83.21   82.82   82.22   77.50   76.61   75.87   74.06
   72.70   70.85   69.54   68.93   68.50   65.88   64.72   63.49   62.09   61.23
   60.55   58.58   57.41   56.56   56.44   55.81   55.03   54.71   54.66   54.66
   54.60   54.60   54.56   54.74   54.76   54.90   54.98   55.62   56.08   56.95
   57.46   57.79   61.74   63.88   64.67   65.75   66.18   67.70   68.30   68.58
   69.11   69.37   69.64   69.68   70.29   71.14   71.31   71.85   73.63   75.65
 -912.17 -915.28 -916.22 -916.79 -917.18 -917.78 -922.50 -923.39 -924.13 -925.94
 -927.30 -929.15 -930.46 -931.07 -931.50 -934.12 -935.28 -936.51 -937.91 -938.77
 -939.45 -941.42 -942.59 -943.44 -943.56 -944.19 -944.97 -945.29 -945.34   52.16
   52.10 -945.40 -945.44 -945.26 -945.24 -945.10 -945.02 -944.38 -943.92 -943.05
 -942.54 -942.21 -938.26 -936.12 -935.33 -934.25 -933.82 -932.30 -931.70 -931.42
 -930.89 -930.63 -930.36 -930.32 -929.71 -928.86 -928.69 -928.15 -926.37 -924.35
BR Coef=-1 , 0 , 0 ,, 0 ,,,0.8,0,1,0,
WSPro=,,,, 1 ,,,, 0 ,,,, 0 ,,,,-1 ,-1 ,-1 , 0 , 0 , 0 , 0 , 0
BC Design=,, 0 ,, 0 ,,,,,,

Type RM Length L Ch R = 1 ,21661.82,229.454300,229.454300,229.454300
XS GIS Cut Line= 3
406359.045628458851521.387856886407333.437989533851664.617023587
408396.806045115851525.728134677
#Sta/Elev= 30
9162.34686.422069208.794 85.21779239.11681.331279299.76180.573659309.86879.88935
9319.97676.427279370.51373.382319441.26571.973699643.41465.046889764.70459.16432
9946.63855.836449966.85353.263039976.96148.686159997.176 43.644510007.2843.73036
10017.3946.87742 10027.552.5544910037.6155.1140410047.7155.4883510199.2155.35471
 10269.856.6599910400.9161.6873210491.6763.76121 10542.166.9307410653.0367.11484
11026.1773.2317511116.9473.1423811137.1175.2956811157.28 81.099611219.6181.76356
#Mann= 3 , 0 , 0
9162.346    0.06       09162.346    0.06       011219.61    0.06       0
#XS Ineff= 2 , 0
       09937.432        10057.41       0
Bank Sta=9162.346,11219.61
Exp/Cntr=0.3,0.1

Type RM Length L Ch R = 1 ,21432.37,710.475000,710.475000,710.475000
XS GIS Cut Line= 3
406322.717031747851732.876851946407334.264462709851785.351809978
408157.181129366851677.712921068
#Sta/Elev= 30
9300.31182.281469322.62482.333849382.70476.729429482.83974.668259492.85271.69481
9522.89370.993319532.90667.478249693.12158.473869773.22958.869289853.33662.68002
9923.43161.089219963.48455.957779973.49853.553559993.52544.3010110003.5443.56915
10033.58 54.486510043.5956.1012410193.7955.0018110293.9356.4995110313.9653.60432
 10354.355.5039910394.6454.7048310445.0757.25833 10697.261.5750210707.2864.15309
10727.4565.6734210929.16 68.379110949.3367.3792111030.0173.2899511143.1475.04773
#Mann= 3 , 0 , 0
9300.311    0.04       09300.311    0.04       011143.14    0.04       0
#XS Ineff= 2 , 0
       09896.272        10181.93       0
Bank Sta=9300.311,11143.14
Exp/Cntr=0.3,0.1

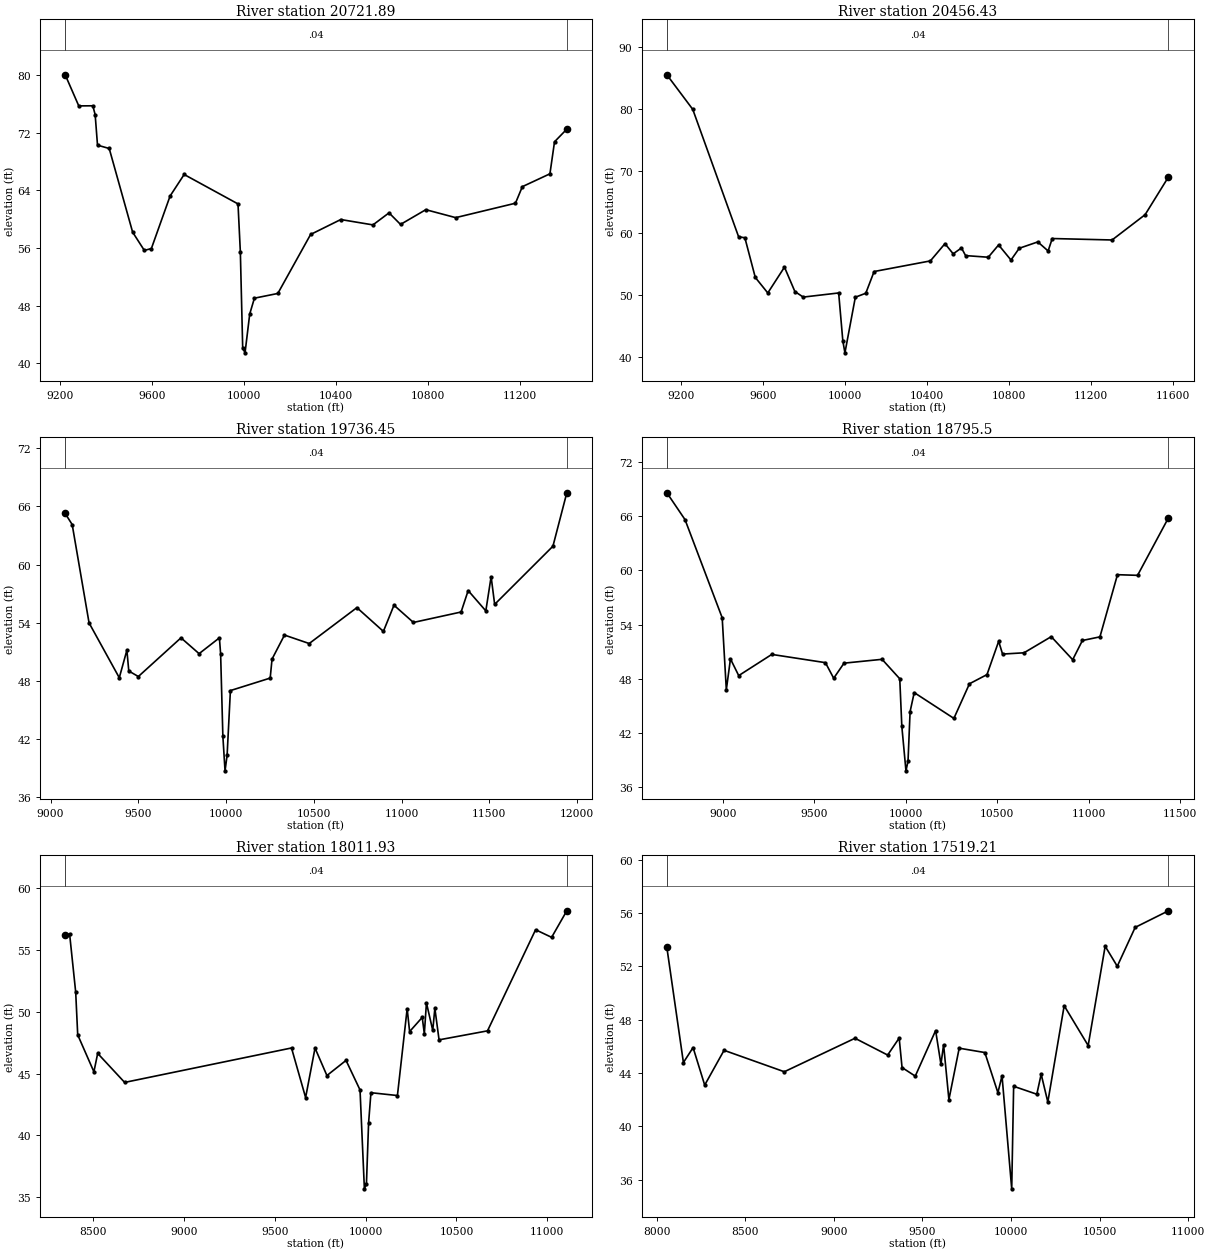
Type RM Length L Ch R = 1 ,20721.89,265.459800,265.459800,265.459800
XS GIS Cut Line= 3
 406366.98786509851863.085185274407480.097796053852080.490698844
408528.446198434852069.682407483
#Sta/Elev= 30
 9221.1180.087439280.21875.759929341.35275.774549351.54174.53992 9361.7370.29843
9412.67569.837799514.56458.201279565.50955.663499596.07655.920399677.58763.23183
9738.721 66.22189973.06762.129429983.25655.452959993.44542.1019710003.6341.42134
10024.0146.8221210044.3949.0209810146.2849.6781610288.92 57.881710420.16 59.9582
10560.1759.2124310630.1760.8868110680.1759.2769510790.1861.3274910920.1860.22153
 11180.262.22684 11210.264.5300511330.2166.3159311350.2170.7702511403.6672.52801
#Mann= 3 , 0 , 0
 9221.11    0.04       0 9221.11    0.04       011403.66    0.04       0
#XS Ineff= 2 , 0
       09805.603        10220.08       0
Bank Sta=9221.11,11403.66
Exp/Cntr=0.3,0.1

Type RM Length L Ch R = 1 ,20456.43,719.980200,719.980200,719.980200
XS GIS Cut Line= 3
406170.785608143852082.189641297 407490.23005259852325.245196834
408588.320330381852199.377141297
#Sta/Elev= 30
9131.67685.453729257.98179.880229481.68259.337649512.18759.184759563.02852.78676
9624.03850.284249705.38454.447859756.22550.512219796.89849.619129969.75850.28523
9990.09542.5519510000.2640.63272 10051.149.6009910101.9550.2361310142.6253.73973
10417.1655.4525910488.1958.2299910528.4556.5921410568.7157.5399310588.8456.30748
10699.5656.0430910749.8958.0245610810.2855.5937710850.5457.4857410941.1358.51413
10991.46 57.053611011.5959.0579511303.4958.8248711464.5462.89975 11578.668.99164
#Mann= 3 , 0 , 0
9131.676    0.04       09131.676    0.04       0 11578.6    0.04       0
#XS Ineff= 2 , 0
       09886.436        10161.56       0
Bank Sta=9131.676,11578.6
Exp/Cntr=0.3,0.1

Type RM Length L Ch R = 1 ,19736.45,940.953000,940.953000,940.953000
XS GIS Cut Line= 6
405897.595588297853049.189793885406515.234260023852786.668383271
 406725.44229269852648.866282597 406793.38284266852563.533883601
406922.557782471 852503.11579445408593.528663695852307.016030192
#Sta/Elev= 30
9083.02465.263669122.93764.122559219.12453.983389391.37648.331089434.68551.16817
9445.51349.027179500.00748.456789743.104 52.44599846.28350.814029961.99652.44418
9968.95250.786929981.75642.300289994.072 38.735410005.9240.3341310024.6647.00818
10251.4748.2968710261.9950.2539910332.9352.7306210473.8651.8582510745.6555.55921
10896.6553.1093610957.0455.8084911067.7754.0317311339.5755.1078711379.8357.31794
 11480.5 55.2244 11510.758.7482711530.8355.8937711863.0261.8907711942.0767.39792
#Mann= 3 , 0 , 0
9083.024    0.04       09083.024    0.04       011942.07    0.04       0
#XS Ineff= 2 , 0
       09782.892        10373.93       0
Bank Sta=9083.024,11942.07
Exp/Cntr=0.3,0.1

Type RM Length L Ch R = 1 , 18795.5,783.566900,783.566900,783.566900
XS GIS Cut Line= 3
406097.000885934853501.460474625407356.060919762852841.326956704
408597.000885934852386.877141282
#Sta/Elev= 30
8693.556 68.60798792.91765.629098996.15754.749219018.73946.768289041.32250.19084
9086.48648.339089267.38850.688569560.71449.774229605.87948.046869662.33449.71893
9870.37850.145059967.19547.986589978.48642.7115310001.0737.7810810012.3638.85446
10023.6544.3460810046.2346.4560810263.1443.5964210348.3447.4337410444.1848.45009
10508.0852.1413610529.38 50.726110646.5250.8672510795.6152.6577810912.7650.10019
10966.0152.2317311061.8552.63512 11157.759.5269111267.6959.4548411436.7165.83719
#Mann= 3 , 0 , 0
8693.556    0.04       08693.556    0.04       011436.71    0.04       0
#XS Ineff= 2 , 0
       09500.258        10300.39       0
Bank Sta=8693.556,11436.71
Exp/Cntr=0.3,0.1

Type RM Length L Ch R = 1 ,18011.93,492.719900,492.719900,492.719900
XS GIS Cut Line= 6
406083.111997038854393.821585745406406.032535344854227.474845365
406921.998847038853876.135365754 407462.78058815853446.075905174
407590.056441486853279.238252416408371.864086121852897.286098614
#Sta/Elev= 30
8346.64356.235478371.02656.305818404.44651.602078415.58648.138648504.70745.14688
8525.50446.636488673.939  44.2869592.257 47.07629669.89843.060089721.73747.06952
9787.14644.843469892.42246.069329969.42443.674499993.40335.6651110004.6936.06869
10016.5440.9983510029.4343.45324 10175.243.2233210228.7850.2571210242.3248.40381
10311.78 49.553610323.3548.2277310334.9350.7292410369.6648.5031910381.2450.28538
10404.3947.7345410671.0748.4634610935.67 56.6541 11023.956.0386611107.4858.19004
#Mann= 3 , 0 , 0
8346.643    0.04       08346.643    0.04       011107.48    0.04       0
#XS Ineff= 2 , 0
       09677.356        10237.12       0
Bank Sta=8346.643,11107.48
Exp/Cntr=0.3,0.1

Type RM Length L Ch R = 1 ,17519.21,546.487900,546.487900,546.487900
XS GIS Cut Line= 6
406159.500885934854685.488252401406686.284499079854453.748688161
407017.813558489854225.363011748 407824.62356773853600.918831185
408029.318579376853362.001653522408433.806441486853046.599363506
#Sta/Elev= 30
8057.522 53.42648150.929  44.7928205.55345.913678271.10243.097598380.35145.70831
8720.42944.099759119.36846.612279303.672 45.35289368.70346.626799384.96144.41472
9459.48443.771349574.423 47.19029604.39644.660859619.38346.125769649.35642.00979
9707.46245.866939852.16245.540889925.935 42.52679949.16743.7949110003.8935.31477
10014.7643.00913 10145.542.4132110170.1243.9141310207.7141.8283410299.9849.05398
10435.3846.0649810531.3153.5170310599.6252.0141310700.6954.9309510888.6956.17659
#Mann= 3 , 0 , 0
8057.522    0.04       08057.522    0.04       010888.69    0.04       0
#XS Ineff= 2 , 0
       0 9757.16         10276.5       0
Bank Sta=8057.522,10888.69
Exp/Cntr=0.3,0.1

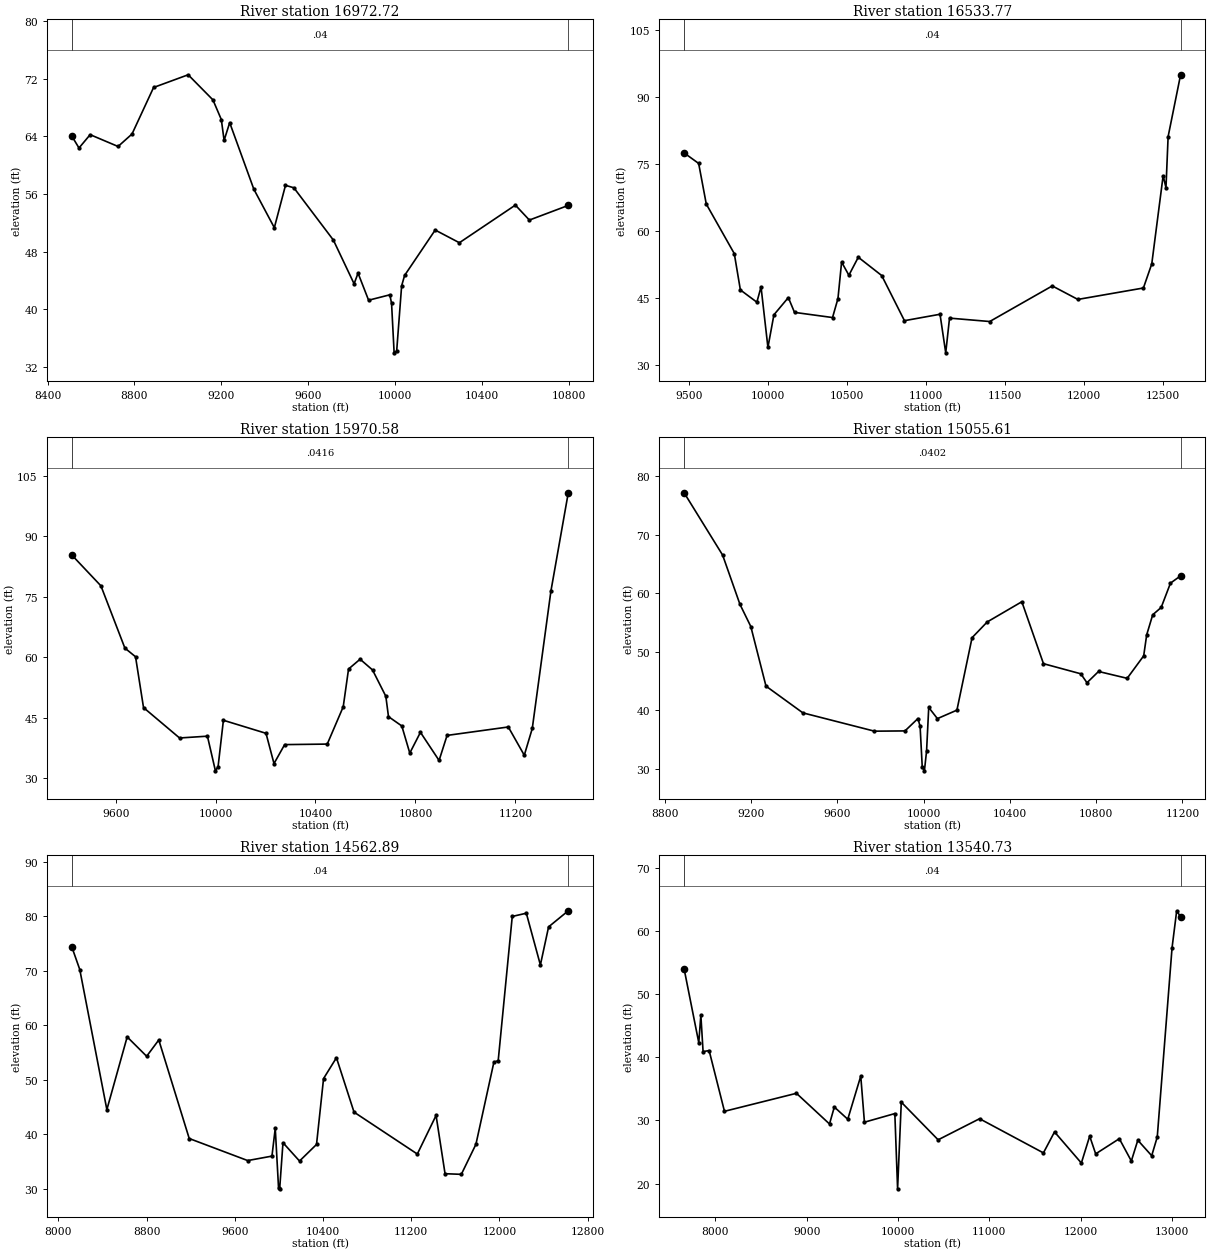
Type RM Length L Ch R = 1 ,16972.72,438.952100,438.952100,438.952100
XS GIS Cut Line= 6
406869.223108143854771.599363521407913.391007215853928.712189078
408048.714203805853845.883861184408066.214287609853836.679219872
408206.028663695853697.814641282408414.361997038853168.300752416
#Sta/Elev= 30
8511.89764.027258545.02562.371368596.43164.219798724.94662.581528789.20464.30983
8888.57570.76606 9047.7872.526639161.89969.043139200.454 66.32019213.30663.42547
9239.00965.88404 9350.2756.653119444.63451.31716 9496.0457.192959534.59556.85118
9716.44149.602669811.96443.53529 9830.18 45.0113 9878.7741.255829976.48942.00639
9984.52240.823569996.33133.9575910008.1434.23226 10030.943.2539210044.5944.69419
10185.4550.9908710296.8349.2294810554.7454.4487110619.2252.3739310798.3554.40755
#Mann= 3 , 0 , 0
8511.897    0.04       08511.897    0.04       010798.35    0.04       0
#XS Ineff= 2 , 0
       09820.866        10192.15       0
Bank Sta=8511.897,10798.35
Exp/Cntr=0.3,0.1

Type RM Length L Ch R = 1 ,16533.77,563.186000,563.186000,563.186000
XS GIS Cut Line= 6
407556.411269575  854572.2339001407826.142741144854357.934485406
  408038.5464333854170.451701134408097.476155639854126.201723635
408406.457034975853953.123030975410140.635145187852793.590104252
#Sta/Elev= 30
 9468.64 77.53529560.64775.182039608.87466.090489786.13654.994819824.69346.86158
 9929.05 44.12219955.402 47.5409    999933.9987410036.8841.2930710128.1745.15199
10167.2241.8385510407.9340.6845810442.2344.9274310465.2853.1042510511.3650.15229
10570.9254.1826510719.0850.0884610863.0139.9823211088.1941.4194911124.2832.78273
11148.3440.5545511402.7439.7948111798.5447.7619311960.4644.7386512375.3447.29747
12428.2352.6914512500.1972.4263312518.1969.7533912531.7281.1832912610.6895.02696
#Mann= 3 , 0 , 0
 9468.64    0.04       0 9468.64    0.04       012610.68    0.04       0
#XS Ineff= 2 , 0
       09944.007        10471.71       0
Bank Sta=9468.64,12610.68
Exp/Cntr=0.3,0.1

Type RM Length L Ch R = 1 ,15970.58,914.973900,914.973900,914.973900
XS GIS Cut Line= 2
407815.635145187854684.215104267409680.218478531853996.715104252
#Sta/Elev= 30
9424.55385.370279541.11577.731119637.03862.299889679.67160.157349711.64547.55816
9855.87540.024779967.43940.471849999.41431.8812810010.0732.9113810031.3944.41492
10201.9241.1821310233.8933.6821410276.5238.3816510447.0538.51248   1051147.75446
10532.3257.1168910578.5359.5486810628.2456.8916310681.5350.3637210692.1945.31369
10745.4843.0050910777.4536.2794710820.0941.4289310894.6934.4554610926.6740.66229
 11171.842.7537911235.7535.7484111267.7342.3776911342.3376.4251611411.84100.7976
#Mann= 3 , 0 , 0
9424.553  0.0416       09424.553  0.0416       011411.84  0.0416       0
#XS Ineff= 2 , 0
       09853.603         10063.9       0
Bank Sta=9424.553,11411.84
Exp/Cntr=0.3,0.1

Type RM Length L Ch R = 1 ,15055.61,492.720000,492.720000,492.720000
XS GIS Cut Line= 6
407797.521719277854789.654919073408762.020568043854686.869330063
408805.229847521854677.188433319408935.463736922  854671.4483805
 409552.73005262854617.779919073 409927.73005259854232.363252416
#Sta/Elev= 30
 8889.1677.139239067.643 66.51149148.09658.098299198.37954.320159268.77544.14825
9439.73839.584979771.60736.460679913.25636.504559973.34738.618049983.34937.29504
 9993.3530.3334610003.3629.6922310013.3733.0611210023.3840.5079710063.6338.60139
10154.0740.0492110224.3152.4119910294.5555.0974810455.0958.5459210555.4447.97744
10728.4546.2509610757.1344.7237310810.8546.6479910943.5545.4787911020.1449.31551
11034.0952.90937   1106256.3230511101.29  57.57311144.3161.7205411191.2562.96501
#Mann= 3 , 0 , 0
 8889.16  0.0402       0 8889.16  0.0402       011191.25  0.0402       0
#XS Ineff= 2 , 0
       09451.781        10255.12       0
Bank Sta=8889.16,11191.25
Exp/Cntr=0.3,0.1

Type RM Length L Ch R = 1 ,14562.89,1022.156100,1022.156100,1022.156100
XS GIS Cut Line= 4
407214.383698434854790.269791752 408240.42536509855014.228125066
409339.383698434854993.394791767 411552.92536512854196.519791767
#Sta/Elev= 30
8122.16174.35825 8194.4470.19998 8440.0944.506058624.32857.842548800.83954.28978
8910.92157.281689186.93739.203929717.03335.158979937.07235.976759967.07841.07731
9997.08330.0825510007.0829.9737810037.09 38.438910187.1235.0727710341.2538.11473
10405.0250.1999910521.9454.0257210681.36 44.045511255.2936.3568611425.3443.43726
11506.7432.7498611654.3632.63328 11786.738.1439311949.5953.2059511988.6453.47976
12116.1779.9366112243.7180.5313212371.2571.0388412445.65 78.026412624.13 80.9772
#Mann= 3 , 0 , 0
8122.161    0.04       08122.161    0.04       012624.13    0.04       0
#XS Ineff= 2 , 0
       09478.269        10424.38       0
Bank Sta=8122.161,12624.13
Exp/Cntr=0.3,0.1

Type RM Length L Ch R = 1 ,13540.73,3327.015300,3327.015300,3327.015300
XS GIS Cut Line= 4
406903.248693079855157.549835145408493.463559538856003.377430633
409960.477448434855812.405208424412087.213559538  855465.1829862
#Sta/Elev= 30
7658.56354.032437819.119 42.33097841.77246.708157866.08140.925297932.38541.08348
8100.32331.452738888.22934.30812 9250.2429.44261  9302.932.133779450.14530.19321
9592.37837.034529632.71629.72404  9965.531.093969995.75319.1577210036.0932.90285
10439.4726.9322910893.2630.2771111592.1824.8568611713.7728.1829612007.61 23.2496
 12098.827.5157812164.2424.7033412423.0427.1075612554.7623.5727112625.6826.86789
12777.6724.4103312838.4727.3729613000.5857.3919313051.2563.2518413094.0262.28434
#Mann= 3 , 0 , 0
7658.563    0.04       07658.563    0.04       013094.02    0.04       0
#XS Ineff= 2 , 0
       09541.564        10919.72       0
Bank Sta=7658.563,13094.02
Exp/Cntr=0.3,0.1