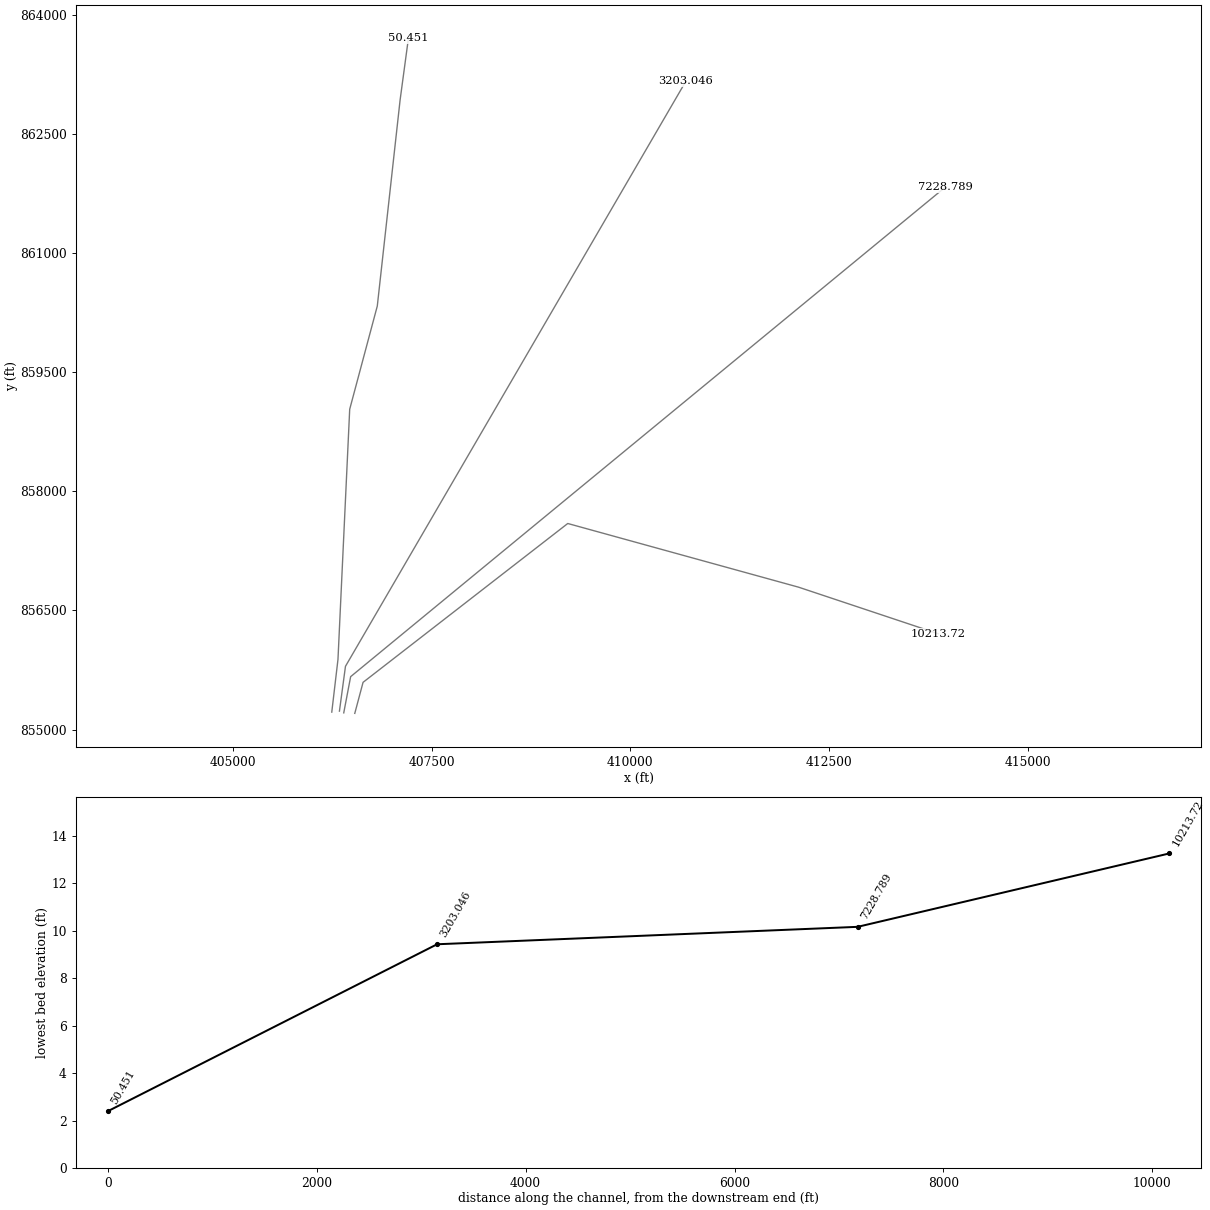
HEC-RAS study 7587_ras.prj: 7587

--- 7587_ras.g01 (geometry) --- (continued)

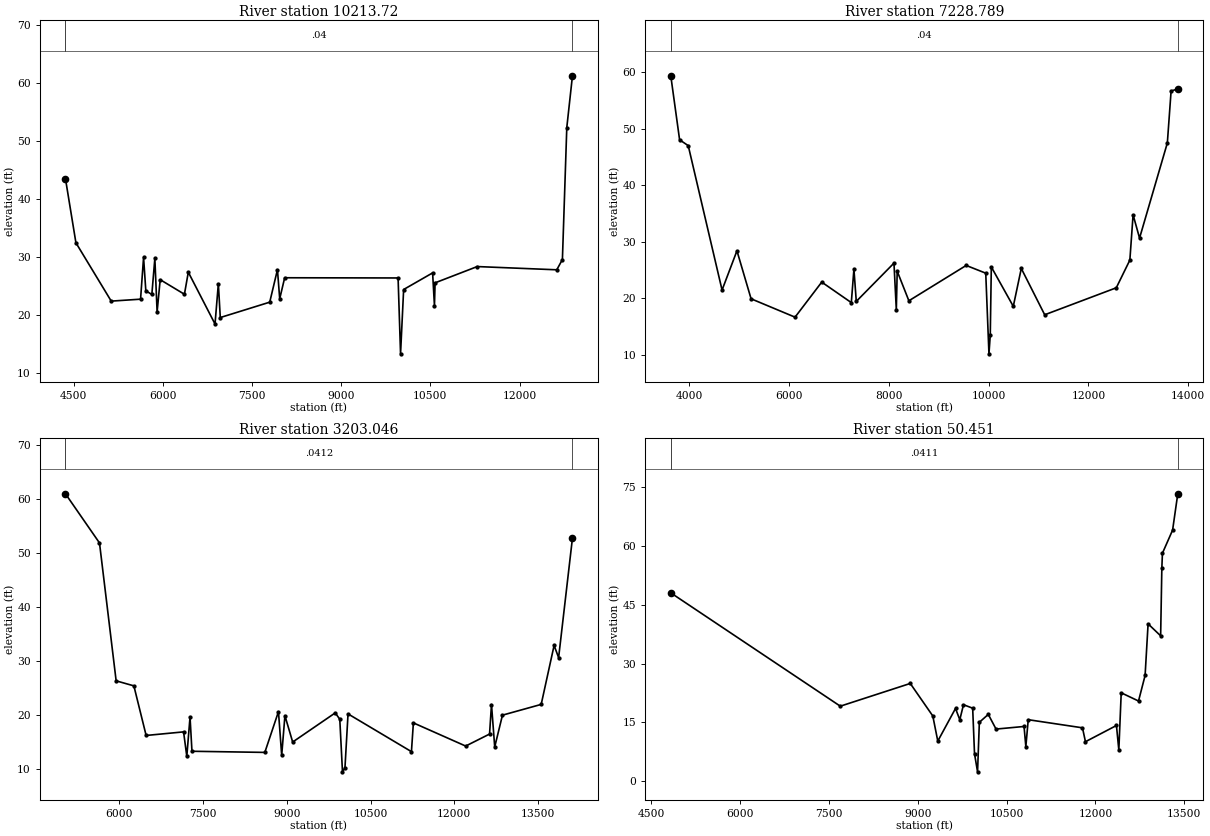
Type RM Length L Ch R = 1 ,10213.72,2984.930900,2984.930900,2984.930900
XS GIS Cut Line= 5
406531.658003986855204.766319543406635.824670643855595.391319528
409212.452274829857594.863252416412117.595503986  856793.3079862
413875.408004045856207.370486185
#Sta/Elev= 30
4358.55343.486374534.73632.421755128.85922.36096 5622.5122.696675673.14129.89294
5711.11524.135655812.376 23.51215863.00729.72006 5900.9820.510755952.92526.06197
6360.71123.545046425.95727.350956875.62618.412476931.61125.36724 6964.2319.52875
7796.11722.180117926.21727.786087964.191 22.76638047.64526.391839956.39626.35641
 9997.8913.2670910049.7624.3649910537.3227.2301510568.4421.5699710578.8125.51572
11288.19  28.32312626.8927.7641612721.7629.5378212795.5552.3091412890.8461.23489
#Mann= 3 , 0 , 0
4358.553    0.04       04358.553    0.04       012890.84    0.04       0
#XS Ineff= 2 , 0
       08074.191        10730.85       0
Bank Sta=4358.553,12890.84
Exp/Cntr=0.3,0.1

Type RM Length L Ch R = 1 ,7228.789,4025.743000,4025.743000,4025.743000
XS GIS Cut Line= 3
 406392.76911515855211.276736185406479.574670643855667.005902871
413966.553837329861830.200347319
#Sta/Elev= 30
 3628.9859.370923805.82748.041553978.88347.006994656.88221.457144955.13828.40167
5238.35719.909826119.48316.658526654.45322.861887247.35619.235977299.56325.15115
7346.76619.448658102.21226.22273 8149.2217.990678166.97424.796098400.97119.55718
9549.58125.812339941.44924.4421210005.8810.1697210032.1213.4791410053.0825.54295
10493.6518.5734310653.8325.2775911123.0217.0805612557.8321.8570712829.8326.75656
12894.59 34.774613024.1130.6483913581.0747.4833213656.2656.6715513790.3257.04615
#Mann= 3 , 0 , 0
 3628.98    0.04       0 3628.98    0.04       013790.32    0.04       0
#XS Ineff= 2 , 0
       08151.777         11218.5       0
Bank Sta=3628.98,13790.32
Exp/Cntr=0.3,0.1

Type RM Length L Ch R = 1 ,3203.046,3152.594700,3152.594700,3152.594700
XS GIS Cut Line= 3
406338.515642881855232.978125095406414.470503986  855797.2142362
410697.782135934863159.367013976
#Sta/Elev= 30
5031.38961.024145641.53851.902465939.81926.318266257.60525.386616477.42216.18344
7148.44316.848497206.28912.305127264.13619.601277298.84413.250928604.455 13.0406
8849.134 20.6033 8906.9812.493328964.82719.856019103.659  14.9649867.23420.37541
 9948.2219.18457 9996.439.43463310040.7710.1474110095.8620.1863811232.4113.18246
11267.1218.5194212204.2414.21788 12632.316.4446112667.0121.9250212724.8614.05745
12863.6919.9510613557.8521.9464313789.2432.8870313870.2230.6288314118.2352.81542
#Mann= 3 , 0 , 0
5031.389  0.0412       05031.389  0.0412       014118.23  0.0412       0
#XS Ineff= 2 , 0
       09023.509        12105.21       0
Bank Sta=5031.389,14118.23
Exp/Cntr=0.3,0.1

Type RM Length L Ch R = 1 ,  50.451,0.000000,0.000000,0.000000
XS GIS Cut Line= 6
406242.052969247855220.709606573406320.086787909855884.152547523
406467.747413695859033.209606558406814.969635934860331.820717677
407102.544064313  862929.1288068 407206.71073097863701.698251233
#Sta/Elev= 30
4832.81248.003077694.08319.123558874.99224.916119255.57416.626799339.55810.22981
9638.571 18.5458 9711.0315.671099773.13819.499559928.40718.613859959.4617.004855
10010.842.39173510041.02 15.019210191.9417.0324210322.7313.28872 10795.613.95428
10825.798.81727210866.0315.6802911781.5913.61054 11831.910.0691112355.07 14.2016
12395.327.95820412435.5622.5329812727.6720.4408312838.6726.9572212889.1240.10427
13101.0237.05688 13121.254.2808313131.2958.1102813302.8363.9981613390.32 73.2561
#Mann= 3 , 0 , 0
4832.812  0.0411       04832.812  0.0411       013390.32  0.0411       0
#XS Ineff= 2 , 0
       09570.874        10218.94       0
Bank Sta=4832.812,13390.32
Exp/Cntr=0.3,0.1